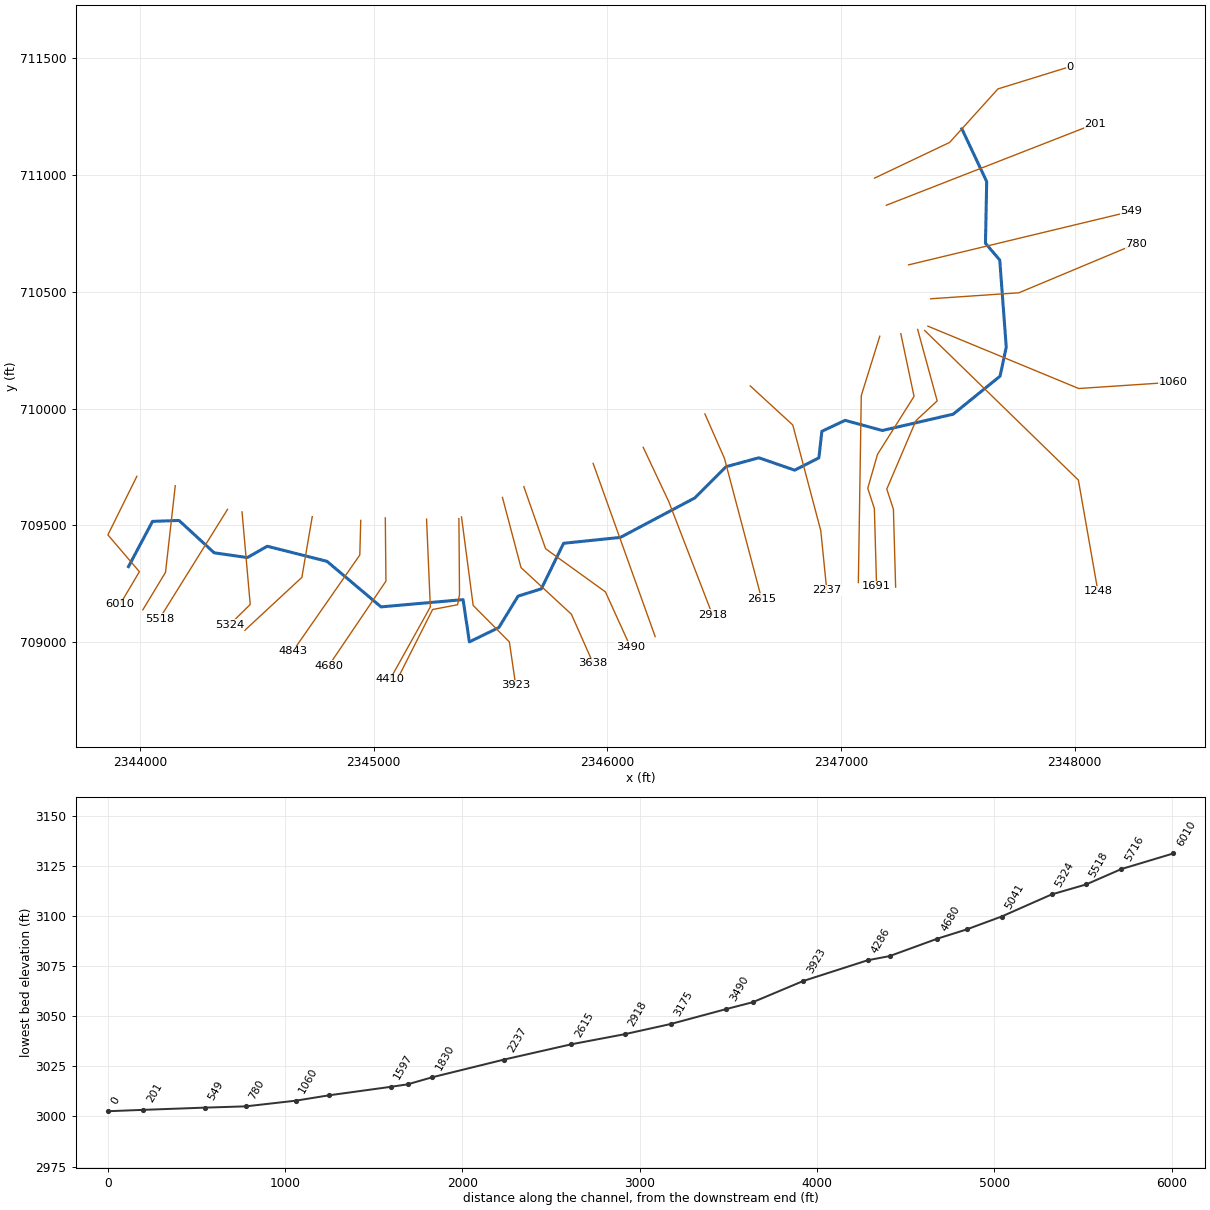
--- CONDONRN.prj (project) ---

Proj Title=CONDONRN
Current Plan=p01
Default Exp/Contr=0,0
English Units
Geom File=g01
Flow File=f01
Plan File=p01
BEGIN DESCRIPTION:
----------MODEL BY WSP USA 2022----------
AFH study
Randolph County, WV
HEC-RAS Version: RAS 6.2
Vertical Datum: NAVD88
Projection: NAD 1983 StatePlane West Virginia S FIPS 4702 (US Feet)
Terrain: 1-meter LIDAR (FEMA Region III 3DEP collected 2016-2018)
Land Use: 2019 NLCD
Hydrologic Method:
WV SIR2010-5033 regression equations
Additional Model Notes:
KWSE at DS Boundary with OTTERCK due to name change
END DESCRIPTION:
DSS Export Rating Curves= 0
DSS Export Rating Curve Sorted= 0
DSS Export Volume Flow Curves= 0
DXF OffsetX= 0
DXF OffsetY= 0
DXF ScaleX= 0
DXF ScaleY= 0

--- CONDONRN.p01 (plan) ---

Plan Title=Floodplain
Program Version=6.20
Short Identifier=Floodplain
Geom File=g01
Flow File=f01
Subcritical Flow
K Sum by GR= 0
Std Step Tol= 0.01
Critical Tol= 0.01
Num of Std Step Trials= 20
Max Error Tol= 0.3
Flow Tol Ratio= 0.001
Split Flow NTrial= 30
Split Flow Tol= 0.02
Split Flow Ratio= 0.02
Log Output Level= 0
Friction Slope Method= 1
Unsteady Friction Slope Method= 2
Unsteady Bridges Friction Slope Method= 1
Parabolic Critical Depth
Global Vel Dist= 0 , 0 , 0
Global Log Level= 0
CheckData=True
Encroach Param=-1 ,0,0, 0
Mapping Interval=1HOUR
Computation Time Step Use Courant=        0
Computation Time Step Use Time Series=    0
Computation Time Step Count To Double=0
Computation Time Step Max Doubling=0
Computation Time Step Max Halving=0
Computation Time Step Residence Courant=0
Run HTab= 0
Run UNet= 0
Run Sediment= 0
Run PostProcess= 0
Run WQNet= 0
Run RASMapper=-1
UNET Theta= 0
UNET Theta Warmup= 0
UNET ZTol= 0
UNET ZSATol= 0
UNET MxIter= 0
UNET Max Iter WO Improvement= 0
UNET MaxInSteps= 0
UNET DtIC= 0
UNET DtMin= 0
UNET MaxCRTS= 0
UNET WFStab= 0
UNET SFStab= 0
UNET WFX= 1
UNET SFX= 1
UNET Gravity=32.174
UNET 1D Methodology=Finite Difference
UNET DSS MLevel= 1
UNET Pardiso=0
UNET DZMax Abort= 0
UNET Use Existing IB Tables= 0
UNET Froude Reduction=False
UNET Froude Limit= 0
UNET Froude Power= 0
UNET D1 Cores= 0
UNET WindReference=Eulerian
UNET WindDragFormulation=Hsu (1988)
UNET D2 Coriolis=0
UNET D2 Cores= 0
UNET D2 Theta= 1
UNET D2 Theta Warmup= 1
UNET D2 Z Tol= 0.01
UNET D2 Volume Tol= 0.01
UNET D2 Max Iterations= 20
UNET D2 Equation= 0
UNET D2 RampUpFraction=0.1
UNET D2 TimeSlices= 1
UNET D2 Turbulence Formulation=Non-Conservative (original)
UNET D2 Eddy Viscosity=0.3
UNET D2 Transverse Eddy Viscosity=0.1
UNET D2 Smagorinsky Mixing=0
UNET D2 BCVolumeCheck=0
UNET D2 Cores=0
UNET D2 SolverType=PARDISO (Direct)
UNET D2 Minimum Iterations= 2147483647
UNET D2 Maximum Iterations= 2147483647
UNET D2 Restart Number= 10
UNET D2 Relaxation Coeff=1.3
UNET D2 SOR Precondition Iterations= 10
UNET D2 ILUT Maximum Fill= 8
UNET D2 ILUT Tolerance=1E-08
UNET D1D2 MaxIter= 0
UNET D1D2 ZTol=0.01
UNET D1D2 QTol=0.1
UNET D1D2 MinQTol=1
Write IC File= 0
Write IC File at Fixed DateTime=0
Write IC File at Sim End=0
Echo Input=False
Echo Parameters=False
Echo Output=False
Write Detailed= 0
HDF Write Warmup=0
HDF Write Time Slices=0
HDF Flush=0
HDF Compression= 1
HDF Chunk Size= 1
HDF Spatial Parts= 1
HDF Use Max Rows=0
HDF Fixed Rows= 1
Calibration Method= 0
Calibration Iterations= 20
Calibration Max Change=0.05
Calibration Tolerance=0.2
Calibration Maximum=1.5
Calibration Minimum=0.5
Calibration Optimization Method= 1
WQ AD Non Conservative
WQ ULTIMATE=-1
WQ Max Comp Step=1HOUR
WQ Output Interval=15MIN
WQ Output Selected Increments= 0
WQ Output face flow=0
WQ Output face velocity=0
WQ Output face area=0
WQ Output face dispersion=0
WQ Output cell volume=0
WQ Output cell surface area=0
WQ Output cell continuity=0
WQ Output cumulative cell continuity=0
WQ Output face conc=0
WQ Output face dconc_dx=0
WQ Output face courant=0
WQ Output face peclet=0
WQ Output face adv mass=0
WQ Output face disp mass=0
WQ Output cell mass=0
WQ Output cell source sink temp=0
WQ Output nsm pathways=0
WQ Output nsm derived pathways=0
WQ Create Restart=0
WQ Fixed Restart=0
WQ System Summary=0
WQ Write To DSS=0
Sorting and Armoring Iterations= 10
XS Update Threshold= 0.02
Bed Roughness Predictor= 0
Hydraulics Update Threshold= 0.02
Energy Slope Method= 1
Volume Change Method= 1
Sediment Retention Method= 0
Sediment TS Multiplier= 1
Warm Up Method= 0
XS Weighting Method= 0
Number of US Weighted Cross Sections= 1
Number of DS Weighted Cross Sections= 1
Upstream XS Weight=0
Main XS Weight=1
Downstream XS Weight=0
Number of DS XS's Weighted with US Boundary= 1
Upstream Boundary Weight= 1
Weight of XSs Associated with US Boundary= 0
Number of US XS's Weighted with DS Boundary= 1
Downstream Boundary Weight= 0.5
Weight of XSs Associated with DS Boundary= 0.5
Percentile Method= 0
Sediment Output Level= 3
Mass or Volume Output= 0
Output Increment Type= 1
Profile and TS Output Increment= 1
Transport Output Increment 1
XS Output Flag= 0
XS Output Increment= 10
Read HDF5 Sediment Hotstart= 0
Sediment Hotstart Type= 0
Write Gradation File= 0
Read Gradation Hotstart= 0
Write HDF5 File= 1
Write Binary Output= 1
Write DSS Sediment File= 0
DSS Sediment Output Type= 1
SV Curve= 0
Specific Gage Flag= 0
Subcell Erosion Methods= 0
Subcell Deposition Methods= 0
Advection Scheme= 1
Matrix Solver= 0
Implicit Weighting Factor= 1
Maximum Outer Loop Convergence Iterations= 5
Convergence Maximum Absolute= 0.001
Convergence RMSE= 0.0001
Grain Fractions Max Abs Error= 0.001
Max Subgrid Regions= 1
Max Subgrid Length Scale= 3.402823E+38
Initial Layer Thickness= 3.402823E+38
Min Layer Thickness= 3.402823E+38
Max Layer Thickness= 3.402823E+38
Number of Layers= 5

--- CONDONRN.f01 (steady flow) ---

Flow Title=Flow
Program Version=6.20
Number of Profiles= 1
Profile Names=P100yr
River Rch & RM=CONDONRN,Main            ,6010
     363
River Rch & RM=CONDONRN,Main            ,1691
     412
River Rch & RM=CONDONRN,Main            ,780
     620
River Rch & RM=CONDONRN,Main            ,0
     730
Boundary for River Rch & Prof#=CONDONRN,Main            , 1
Up Type= 0
Dn Type= 1
Dn Known WS=3004.9
DSS Import GetInterval= 0
DSS Import GetPeak= 0
DSS Import FillOption= 0

--- CONDONRN.g01 (geometry) ---

Geom Title=Geometry
Program Version=6.20

River Reach=CONDONRN        ,Main
Reach XY= 30
2343951.24499999709323.4790000022344054.11000001709517.055000022
2344167.39100003 709520.961000012344317.99900003709382.506000012
2344459.49200001709362.106999993     2344544.995709410.717999995
2344800.63699999709346.0480000082345031.97400002709151.170000002
2345383.01615063709182.227083908     2345410.013709001.430000007
2345535.88100003709062.6280000212345618.34599999709197.177000001
2345717.73800004709228.4270000162345813.22400004709423.305000022
2346056.28000005709448.4790000172346374.42200001709617.314999998
2346508.10300003709750.996000007     2346648.728709789.190000013
2346802.07500002709736.1850000022346905.48500004709788.849999994
2346918.25900003709902.4720000182347017.65100002709949.347000003
2347176.94000001709905.9440000212347480.19499998709975.724000007
2347680.88899998 710138.571000012347707.27800003710262.703000009
2347679.50092091710635.2737050772347618.35984302710707.153832008
2347623.60199998710971.0550000072347517.42145497711196.698177412

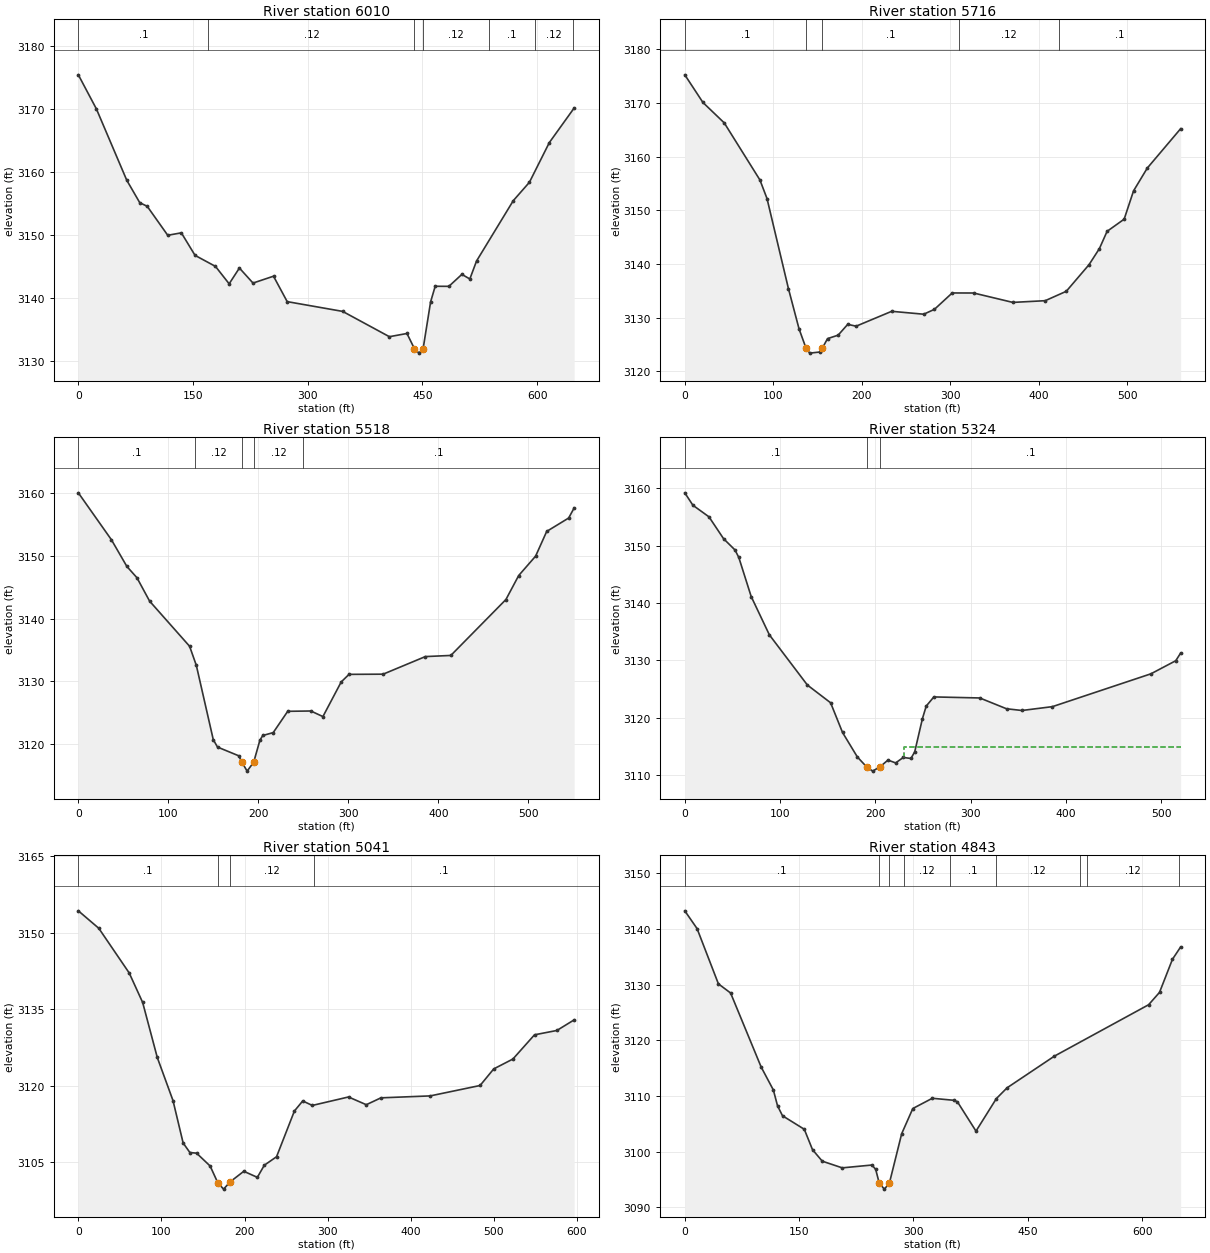
Type RM Length L Ch R = 1 ,6010    ,301.4,293.8,284.4
XS GIS Cut Line= 4
2343987.04801168709709.9347156242343863.08276672709459.309329068
 2343997.8275982709301.6578762342343915.63325099709162.870699808
#Sta/Elev= 30
       0 3175.42    23.6 3170.01    63.3 3158.68    80.3 3155.11    90.1 3154.53
   116.9 3149.93   134.7 3150.32   152.6 3146.74   179.3 3144.99   197.2 3142.22
   210.6 3144.73   228.4 3142.34   255.2 3143.43   273.1 3139.39   345.6 3137.84
   406.7 3133.82   429.7 3134.33  439.483131.906   445.5 3131.21   450.8  3131.9
   460.6 3139.35   466.6 3141.83   484.5 3141.82   501.5 3143.72   511.9 3142.99
   520.7 3145.85   568.7 3155.43   589.8 3158.35   615.8 3164.65   648.3 3170.15
#Mann= 7 ,-1,0
       0      .1       0     170     .12       0  439.48    .045       0
   450.8     .12       0     537      .1       0     597     .12       0
     647      .1       0
Bank Sta=439.48,450.8
XS Rating Curve= 0 ,0
Exp/Cntr(USF)=0,0
Exp/Cntr=0.3,0.1

Type RM Length L Ch R = 1 ,5716    ,202.5,198.5,193.1
XS GIS Cut Line= 3
2344151.43670609709669.5112661792344109.66580833709298.962979605
2344012.64952966709138.616630142
#Sta/Elev= 30
       0 3175.25    20.5  3170.1    44.6 3166.29    84.9 3155.66    92.9  3152.2
   117.1 3135.43   129.1 3127.92   137.1 3124.27   141.2  3123.4   153.3 3123.62
   155.43124.329   161.3  3126.1   173.3 3126.75   184.1 3128.76   193.6 3128.42
   233.8 3131.19     270 3130.65   282.1 3131.56   302.2 3134.61   326.4  3134.6
   370.7 3132.85   407.3 3133.17   431.1 3134.92   456.8 3139.88   468.5 3142.87
   477.2 3146.09   496.5 3148.36   507.1 3153.63   522.6 3157.87   560.3 3165.21
#Mann= 5 ,-1,0
       0      .1       0   137.1    .045       0   155.4      .1       0
     310     .12       0   422.9      .1       0
Bank Sta=137.1,155.4
XS Rating Curve= 0 ,0
Exp/Cntr(USF)=0,0
Exp/Cntr=0.3,0.1

Type RM Length L Ch R = 1 ,5518    ,190,194.3,198.6
XS GIS Cut Line= 2
2344375.11312635709568.4526425682344084.06429035709100.888077327
#Sta/Elev= 30
       0 3160.02    36.8 3152.54    53.9 3148.31    65.1 3146.51    79.2 3142.78
   123.6  3135.6   131.1 3132.55   149.9 3120.74   154.6 3119.56   178.2 3118.17
   181.7 3117.15   187.5 3115.73   194.8 3117.15   201.7 3120.65   204.9  3121.4
   216.5 3121.86   232.6 3125.25   258.3  3125.3   271.7 3124.41     292 3129.92
   300.7 3131.13   338.6 3131.16   385.5 3133.96   413.8 3134.14     475 3143.04
   489.2 3146.86     508 3149.95   520.3 3153.88   544.7 3156.01   550.8 3157.62
#Mann= 5 ,-1,0
       0      .1       0     130     .12       0   181.7    .045       0
   194.8     .12       0     250      .1       0
Bank Sta=181.7,194.8
XS Rating Curve= 0 ,0
Exp/Cntr(USF)=0,0
Exp/Cntr=0.3,0.1

Type RM Length L Ch R = 1 ,5324    ,283.1,282.5,278.5
XS GIS Cut Line= 3
2344437.09574883 709557.673056052344472.12940501709161.523251493
2344384.54526455709075.286559345
#Sta/Elev= 30
       0 3159.17     8.5 3157.01    25.4 3154.99    40.7 3151.19    52.7 3149.23
    56.7 3147.93    69.7 3141.13    88.8 3134.46   128.7 3125.73   153.1 3122.64
   165.6 3117.48   181.2 3113.21  190.873111.495   197.3 3110.75   205.3 3111.55
   213.3 3112.67   221.4 3112.18   229.4 3113.13   237.4 3112.95   241.4  3114.1
   249.5 3119.88   253.5 3122.07   261.5 3123.66   309.7 3123.48   337.8  3121.6
     354  3121.3     386 3121.97   489.4 3127.68   515.5 3129.96   520.6 3131.29
#Mann= 3 ,-1,0
       0      .1       0  190.87    .045       0   205.3      .1       0
#XS Ineff= 2 , 0
                          229.99         3115.02
Permanent Ineff=
       F       F
Bank Sta=190.87,205.3
XS Rating Curve= 0 ,0
Exp/Cntr(USF)=0,0
Exp/Cntr=0.3,0.1

Type RM Length L Ch R = 1 ,5041    ,199.8,197.6,193.4
XS GIS Cut Line= 3
2344737.57672303709537.4613313272344693.11092864709277.403806568
2344449.22278366709051.032489679
#Sta/Elev= 30
       0 3154.29    24.6 3150.87    61.2 3142.11    77.4 3136.32      95 3125.53
   113.9 3117.09   126.1 3108.77   134.2  3106.9   142.3 3106.77   158.6 3104.25
   167.8 3100.97   174.8 3099.72  182.493101.126   199.1 3103.22   215.4 3102.03
   223.8 3104.41   238.5 3106.07     260 3115.04     270 3117.01   281.5 3116.13
   325.1 3117.79   346.5 3116.27   364.1 3117.62   423.4    3118   483.4 3120.04
   499.8 3123.29   522.9 3125.23   548.9 3129.98   575.8 3130.83   596.6 3132.91
#Mann= 4 ,-1,0
       0      .1       0   167.8    .045       0  182.49     .12       0
  283.83      .1       0
Bank Sta=167.8,182.49
XS Rating Curve= 0 ,0
Exp/Cntr(USF)=0,0
Exp/Cntr=0.3,0.1

Type RM Length L Ch R = 1 ,4843    ,163.1,163.9,163.5
XS GIS Cut Line= 3
2344945.08376351709521.2919515492344941.04141857 709373.07263692
2344654.03492751708960.753452586
#Sta/Elev= 30
       0 3143.25    16.1 3140.06    44.1 3130.13    60.1 3128.49   100.2 3115.19
   116.2 3111.07   121.7 3108.22   128.2 3106.44   156.8 3104.01   167.6 3100.34
   180.4 3098.28   206.6 3097.08   245.6 3097.59   250.5  3096.8   255.1 3094.35
   261.8 3093.26  268.363094.286   284.6 3103.22   299.2 3107.74   324.8 3109.58
   352.8 3109.22   357.7 3108.95   382.1 3103.68   408.8 3109.52   422.9 3111.46
     485 3117.15   608.6 3126.38   622.9  3128.6   639.9 3134.55   650.6 3136.76
#Mann= 9 ,-1,0
       0      .1       0   255.1    .045       0  268.36      .1       0
  288.27     .12       0  348.27      .1       0  408.27     .12       0
  518.27      .1       0  528.27     .12       0  648.27      .1       0
Bank Sta=255.1,268.36
XS Rating Curve= 0 ,0
Exp/Cntr(USF)=0,0
Exp/Cntr=0.3,0.1

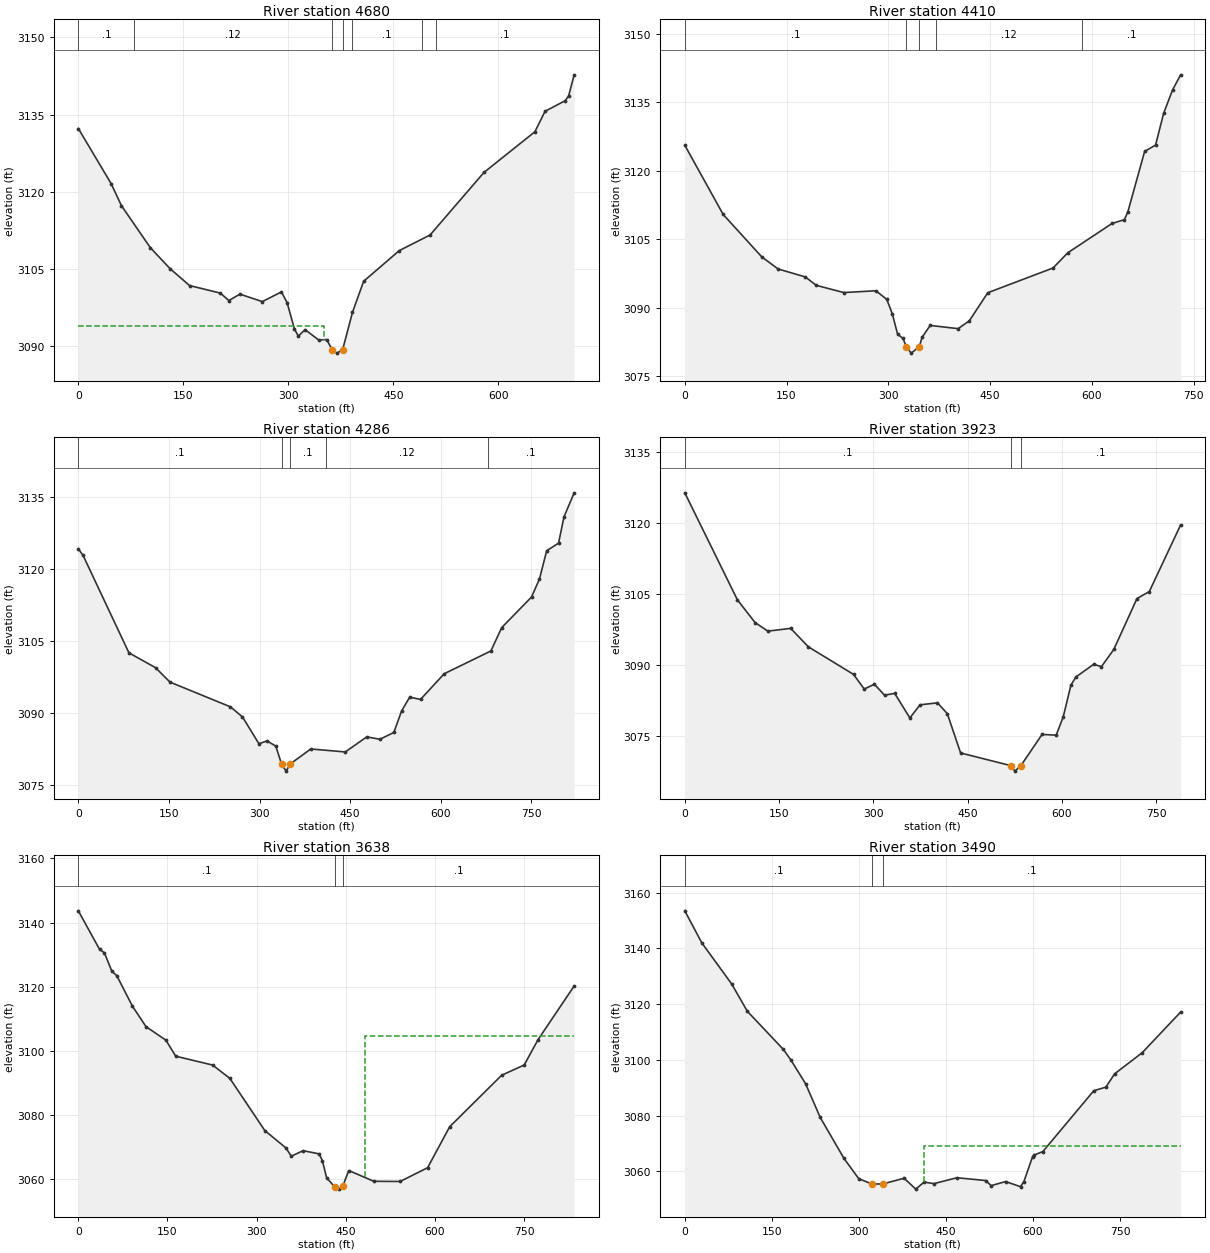
Type RM Length L Ch R = 1 ,4680    ,263.4,269.6,271.9
XS GIS Cut Line= 3
2345050.18473207709532.071538068 2345052.8796287 709261.23442679
 2344807.6440354708898.770830104
#Sta/Elev= 30
       0 3132.29    46.9 3121.59    61.5 3117.33   102.9 3109.16   130.9 3105.11
   158.9 3101.81   202.9 3100.34   215.1  3098.9   230.9 3100.14   262.9 3098.69
   290.2 3100.57   298.3  3098.5   308.8 3093.38   314.4 3091.98     324 3093.25
   343.4 3091.25   354.9 3091.32   362.7 3089.35   369.3 3088.69  377.613089.313
   391.7 3096.59   407.7 3102.64   458.6 3108.59   502.7 3111.63   579.6 3123.76
   652.4 3131.66   666.9 3135.63   695.9  3137.7   700.7 3138.67   708.5 3142.71
#Mann= 7 ,-1,0
       0      .1       0      80     .12       0   362.7    .045       0
  377.61     .12       0  390.85      .1       0  490.85     .12       0
  510.85      .1       0
#XS Ineff= 2 , 0
          350.82 3094.05
Permanent Ineff=
       F       F
Bank Sta=362.7,377.61
XS Rating Curve= 0 ,0
Exp/Cntr(USF)=0,0
Exp/Cntr=0.3,0.1

Type RM Length L Ch R = 1 ,4410    ,125.2,123.7,121.5
XS GIS Cut Line= 3
2345226.70046131709526.6817448092345242.86984109709150.743664975
2345070.39645679708840.830552567
#Sta/Elev= 30
       0  3125.6    56.6 3110.41   113.6 3101.09   137.6 3098.45   177.7 3096.71
   193.7 3094.87   234.3 3093.28   281.8 3093.67   297.8 3091.78   305.8 3088.68
   313.8 3084.12   321.8 3083.21   326.4 3081.44   333.8 3079.99   345.8 3081.43
   349.8 3083.45   361.8 3086.07   402.9 3085.36   419.3 3087.04   446.7 3093.24
   542.9 3098.67   564.7 3102.01   629.9 3108.44   648.2 3109.28   653.3 3111.04
   677.9 3124.23   694.1 3125.65   705.9 3132.57   719.1 3137.73     731 3141.05
#Mann= 5 ,-1,0
       0      .1       0   326.4    .045       0   345.8      .1       0
     370     .12       0  586.29      .1       0
Bank Sta=326.4,345.8
XS Rating Curve= 0 ,0
Exp/Cntr(USF)=0,0
Exp/Cntr=0.3,0.1

Type RM Length L Ch R = 1 ,4286    ,353.8,363.2,368
XS GIS Cut Line= 5
2345365.14663909709528.9695714832345367.72353249 709203.92985324
2345359.51677114709160.2656355872345252.55956652709139.977986463
2345098.05954981708834.133810496
#Sta/Elev= 30
       0 3124.15     7.8 3122.81    83.8 3102.52   127.8 3099.44   151.8 3096.43
   251.8 3091.29   271.8 3089.19   299.1  3083.6   312.4  3084.2     327 3083.11
  336.42 3079.41   344.1 3077.91     351 3079.41   384.9 3082.52   442.1  3081.9
   477.6 3085.04   499.4 3084.54   522.4 3085.95   535.3 3090.44   548.7  3093.3
   566.6 3092.83   605.8 3098.17   683.2 3102.92     701 3107.77   750.4 3114.14
   763.6 3117.91   775.5 3123.77   795.2 3125.35   804.1  3130.8     821 3135.82
#Mann= 5 ,-1,0
       0      .1       0  336.42    .045       0     351      .1       0
  409.48     .12       0  678.34      .1       0
Bank Sta=336.42,351
XS Rating Curve= 0 ,0
Exp/Cntr(USF)=0,0
Exp/Cntr=0.3,0.1

Type RM Length L Ch R = 1 ,3923    ,284.5,285,284.6
XS GIS Cut Line= 4
2345376.26722425709536.113883012 2345426.1228119709157.480906549
2345581.07936811 709001.17690203 2345608.0283344708816.576482901
#Sta/Elev= 30
       0 3126.29    83.7  3103.7   111.9  3098.9   132.1 3097.11   168.4 3097.69
   196.6 3093.79   268.4 3087.98   285.4 3084.89   301.5  3085.9   317.7  3083.6
   333.8 3083.97     358 3078.79   374.1 3081.56   401.9 3081.98   417.5  3079.7
   438.7  3071.4  518.62 3068.73     525 3067.57   534.4 3068.69   568.2 3075.32
   590.7 3075.15     602 3079.07   614.1 3085.71     622 3087.43   650.4 3090.12
   662.6 3089.61   682.3 3093.24   719.2 3103.99   738.8 3105.46   788.6 3119.52
#Mann= 3 ,-1,0
       0      .1       0  518.62    .045       0   534.4      .1       0
Bank Sta=518.62,534.4
XS Rating Curve= 0 ,0
Exp/Cntr(USF)=0,0
Exp/Cntr=0.3,0.1

Type RM Length L Ch R = 1 ,3638    ,148.3,148.5,148.3
XS GIS Cut Line= 4
2345551.43550518709619.6556785312345630.93495575709319.174704327
2345846.52668613709119.7523537342345939.50061985708909.550416623
#Sta/Elev= 30
       0 3143.68    35.7 3131.68    43.9 3130.61    56.4 3124.85    64.6 3123.51
      91 3113.99   113.9 3107.59   147.4 3103.38   163.9 3098.39     226 3095.63
     255 3091.47   313.8 3075.22   349.1 3069.85   358.4 3067.23   378.2 3068.96
   405.1 3067.97   410.6 3065.87   417.8 3060.51   431.6 3057.63   437.8 3056.98
  444.783057.829   455.1 3062.78   497.1 3059.42   541.4 3059.36   587.7 3063.65
   624.8  3076.4   712.3 3092.46   750.2 3095.64   773.5 3103.54   834.3 3120.26
#Mann= 3 ,-1,0
       0      .1       0   431.6    .045       0  444.78      .1       0
#XS Ineff= 2 , 0
                          481.59         3104.76
Permanent Ineff=
       F       F
Bank Sta=431.6,444.78
XS Rating Curve= 0 ,0
Exp/Cntr(USF)=0,0
Exp/Cntr=0.3,0.1

Type RM Length L Ch R = 1 ,3490    ,316,314.5,304.7
XS GIS Cut Line= 4
2345643.06199059709665.4689212352345736.03592431709400.021603216
2345992.05110413709215.421184086  2346098.499521708980.965177308
#Sta/Elev= 30
       0 3153.47    29.4 3141.94    80.8 3127.21   107.8 3117.41   169.8 3103.73
   182.6 3099.99     208 3091.47   233.4  3079.3   274.2 3064.63   299.8 3057.31
  322.413055.442   340.8 3055.42     378 3057.49     398 3053.58   412.3  3056.1
   429.4 3055.55   468.8 3057.67   518.4 3056.67     528 3054.83   552.7  3056.3
   578.5 3054.46   584.3 3056.27   599.3 3065.26   601.7 3065.81   616.9 3067.04
   704.8 3088.91   725.6 3090.19   740.7 3094.97   788.2 3102.55   854.4 3117.13
#Mann= 3 ,-1,0
       0      .1       0  322.41    .045       0   340.8      .1       0
#XS Ineff= 2 , 0
                          411.72         3069.09
Permanent Ineff=
       F       F
Bank Sta=322.41,340.8
XS Rating Curve= 0 ,0
Exp/Cntr(USF)=0,0
Exp/Cntr=0.3,0.1

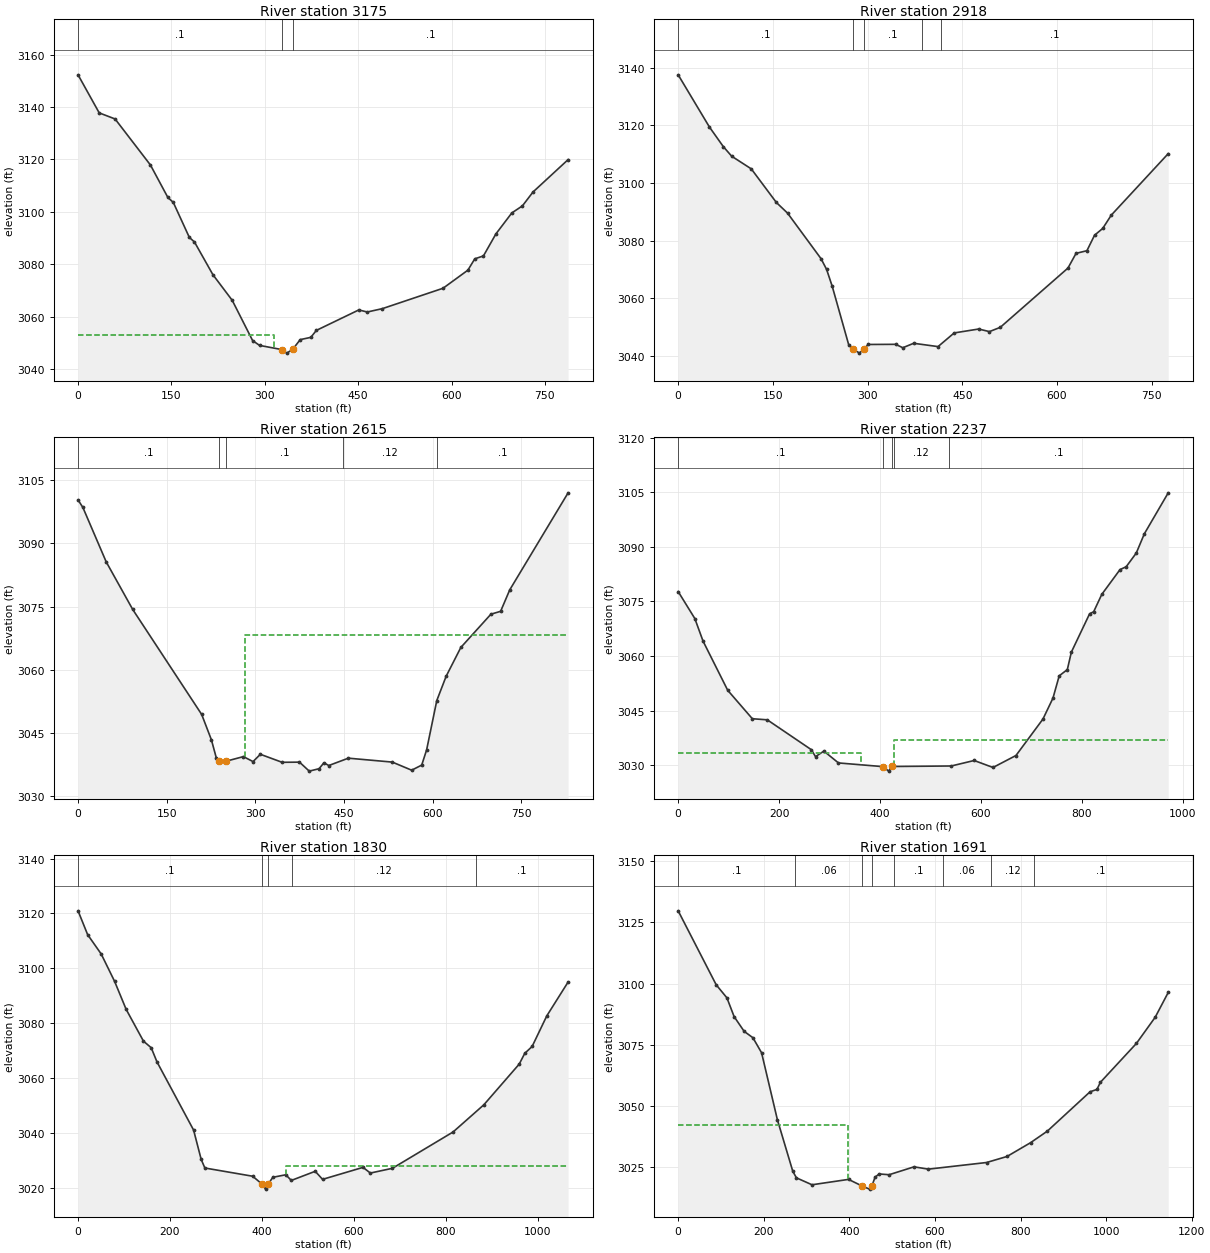
Type RM Length L Ch R = 1 ,3175    ,255.9,257.1,256.2
XS GIS Cut Line= 2
2345939.50061985709765.1800965312346204.94793787709024.083523382
#Sta/Elev= 30
       0 3152.28      34 3137.76    59.5 3135.44   116.3 3117.87   144.3 3105.48
     153 3103.61   178.8 3090.24     187 3088.51   216.7    3076   247.7 3066.23
   280.4  3050.9   291.5 3049.05   327.2 3047.46   335.3  3046.1   344.6  3047.5
   356.9 3051.25   373.9 3052.12   382.8 3054.77     451 3062.58   464.6 3061.79
   488.8 3063.07   586.3 3070.85   626.2 3077.75   637.3 3082.08   651.2 3083.19
   671.3 3091.61   696.8 3099.59   713.8 3102.28   730.8 3107.57   787.2 3119.93
#Mann= 3 ,-1,0
       0      .1       0   327.2    .045       0   344.6      .1       0
#XS Ineff= 2 , 0
          313.97 3052.95
Permanent Ineff=
       F       F
Bank Sta=327.2,344.6
XS Rating Curve= 0 ,0
Exp/Cntr(USF)=0,0
Exp/Cntr=0.3,0.1

Type RM Length L Ch R = 1 ,2918    ,303.3,302.8,303.4
XS GIS Cut Line= 3
 2346153.7449019709833.899960587 2346262.8882154709602.138850438
2346450.18353116709117.057457105
#Sta/Elev= 30
       0  3137.5    49.4 3119.45    71.5 3112.62    84.8 3109.29   115.8 3104.91
   155.5 3093.27   173.2 3089.59   226.3 3073.78   235.1 3070.07     244 3064.22
   270.1 3043.96   276.6 3042.53   287.2 3041.06  294.223042.603   301.2 3044.06
   344.5 3044.11   355.8 3042.93     373 3044.47   411.6 3043.32   437.2 3048.06
   475.9 3049.41     493 3048.52   510.2    3050   617.4 3070.54   630.2 3075.64
   647.4 3076.55   659.5 3081.92   672.4 3084.26     686 3088.88   776.2 3110.19
#Mann= 5 ,-1,0
       0      .1       0   276.6    .045       0  294.22      .1       0
  386.17     .12       0  416.17      .1       0
Bank Sta=276.6,294.22
XS Rating Curve= 0 ,0
Exp/Cntr(USF)=0,0
Exp/Cntr=0.3,0.1

Type RM Length L Ch R = 1 ,2615    ,373.5,378,375.1
XS GIS Cut Line= 3
2346417.84477161709976.7294819572346501.38656713709786.739269568
2346660.38546827 709185.77732116
#Sta/Elev= 30
       0 3100.26     8.2 3098.47    47.6 3085.59    92.5  3074.3   209.2 3049.42
   225.7 3043.39   233.9 3039.15   238.1 3038.36   250.5 3038.34   279.8 3039.43
   296.1 3038.25   308.5 3039.98   345.3 3038.08   374.7 3038.12   391.2 3035.99
   407.8 3036.56     416 3037.96   424.3 3037.32   457.4 3039.06   531.8 3038.13
   564.5 3036.21   581.5 3037.42   589.8 3041.02     607 3052.71   622.9 3058.49
   647.7  3065.3   698.6 3073.18     715 3073.86   730.5 3078.96   829.2 3101.94
#Mann= 5 ,-1,0
       0      .1       0   238.1    .045       0   250.5      .1       0
  447.55     .12       0  607.55      .1       0
#XS Ineff= 2 , 0
                          282.31         3068.34
Permanent Ineff=
       F       F
Bank Sta=238.1,250.5
XS Rating Curve= 0 ,0
Exp/Cntr(USF)=0,0
Exp/Cntr=0.3,0.1

Type RM Length L Ch R = 1 ,2237    ,401.6,406.7,400.8
XS GIS Cut Line= 4
2346611.87732894710096.6523819762346793.78285144709929.568790939
2346913.70575146 709476.826157162346939.30726944 709222.15842566
#Sta/Elev= 30
       0  3077.7      33  3070.3    49.3  3064.1    98.2 3050.59     147 3042.78
   176.6 3042.48     264 3034.27   272.2 3032.37   288.8 3033.89   317.7 3030.64
   406.3 3029.62   417.1 3028.39  423.283029.663   541.2  3029.8   586.7 3031.31
     624 3029.39   669.5 3032.68     723 3042.69   742.9 3048.46   755.2 3054.56
   771.3 3056.27   779.3 3061.07   815.5 3071.61   823.5 3072.16   839.6 3076.93
   875.8 3083.75   887.9 3084.51     908 3088.29     924 3093.58   971.3 3104.82
#Mann= 5 ,-1,0
       0      .1       0   406.3    .045       0  423.28      .1       0
     427     .12       0     537      .1       0
#XS Ineff= 2 , 0
          361.44 3033.42  427.96         3036.96
Permanent Ineff=
       F       F
Bank Sta=406.3,423.28
XS Rating Curve= 0 ,0
Exp/Cntr(USF)=0,0
Exp/Cntr=0.3,0.1

Type RM Length L Ch R = 1 ,1830    ,141.4,139.4,135.5
BEGIN DESCRIPTION:
Structure XS 4
END DESCRIPTION:
XS GIS Cut Line= 3
2347166.03219894710309.1715345322347086.92190608710055.185857439
 2347074.4308072709254.922789614
#Sta/Elev= 30
       0 3120.97    20.9 3112.28    50.3 3105.26    79.6 3095.24   104.7 3085.05
   142.4 3073.46   159.2 3071.07   171.8  3065.9   251.4 3041.07     268 3030.34
     276 3027.23     380 3024.23  400.57 3021.34     408 3019.53  413.48 3021.34
     424 3023.85   452.1 3024.76   464.1  3022.7   516.1 3026.03   532.1 3023.09
   620.1 3027.46   636.1 3025.39   684.1 3027.12   816.1 3040.36     883 3050.26
   960.1 3065.12   972.1 3069.03   988.1 3071.53  1020.1  3082.7  1066.4 3095.02
#Mann= 5 ,-1,0
       0      .1       0  400.57    .045       0  413.48      .1       0
  466.02     .12       0  866.02      .1       0
#XS Ineff= 2 , 0
                          452.21         3028.11
Permanent Ineff=
       F       F
Bank Sta=400.57,413.48
XS Rating Curve= 0 ,0
Exp/Cntr(USF)=0,0
Exp/Cntr=0.3,0.1

Type RM Length L Ch R = 1 ,1691    ,101.2,94.3,88.4
BEGIN DESCRIPTION:
Structure XS 3
END DESCRIPTION:
XS GIS Cut Line= 6
2347256.12397507710320.0533978472347312.71680429710051.911183199
2347156.41279977709803.9806932732347114.64190201709658.456275272
2347142.93831662709572.2195831242347152.47581087709238.649418616
#Sta/Elev= 30
       0 3129.75    88.8 3099.53   113.9 3094.18   130.7 3086.52   154.2 3080.48
   174.7 3077.87   194.9 3071.73   231.9 3044.32   267.9 3023.25   276.4  3020.6
   312.7 3017.77   398.1 3019.97  429.63 3017.28   447.1 3015.99  452.58 3017.27
   460.2 3020.91   469.7 3022.19   492.9 3021.88   551.1  3025.1   584.7 3024.16
   720.6 3026.87   768.3 3029.33   823.3 3034.96   862.5 3039.68   962.5 3055.79
   978.5 3056.74   986.5 3059.64  1070.6 3075.52  1114.6 3086.24  1145.1 3096.39
#Mann= 8 ,-1,0
       0      .1       0  274.05     .06       0  429.63    .045       0
  452.58     .06       0  504.81      .1       0  619.25     .06       0
  730.65     .12       0  831.41      .1       0
#XS Ineff= 2 , 0
          396.82    3042
Permanent Ineff=
       F       F
Bank Sta=429.63,452.58
XS Rating Curve= 0 ,0
Exp/Cntr(USF)=0,0
Exp/Cntr=0.3,0.1

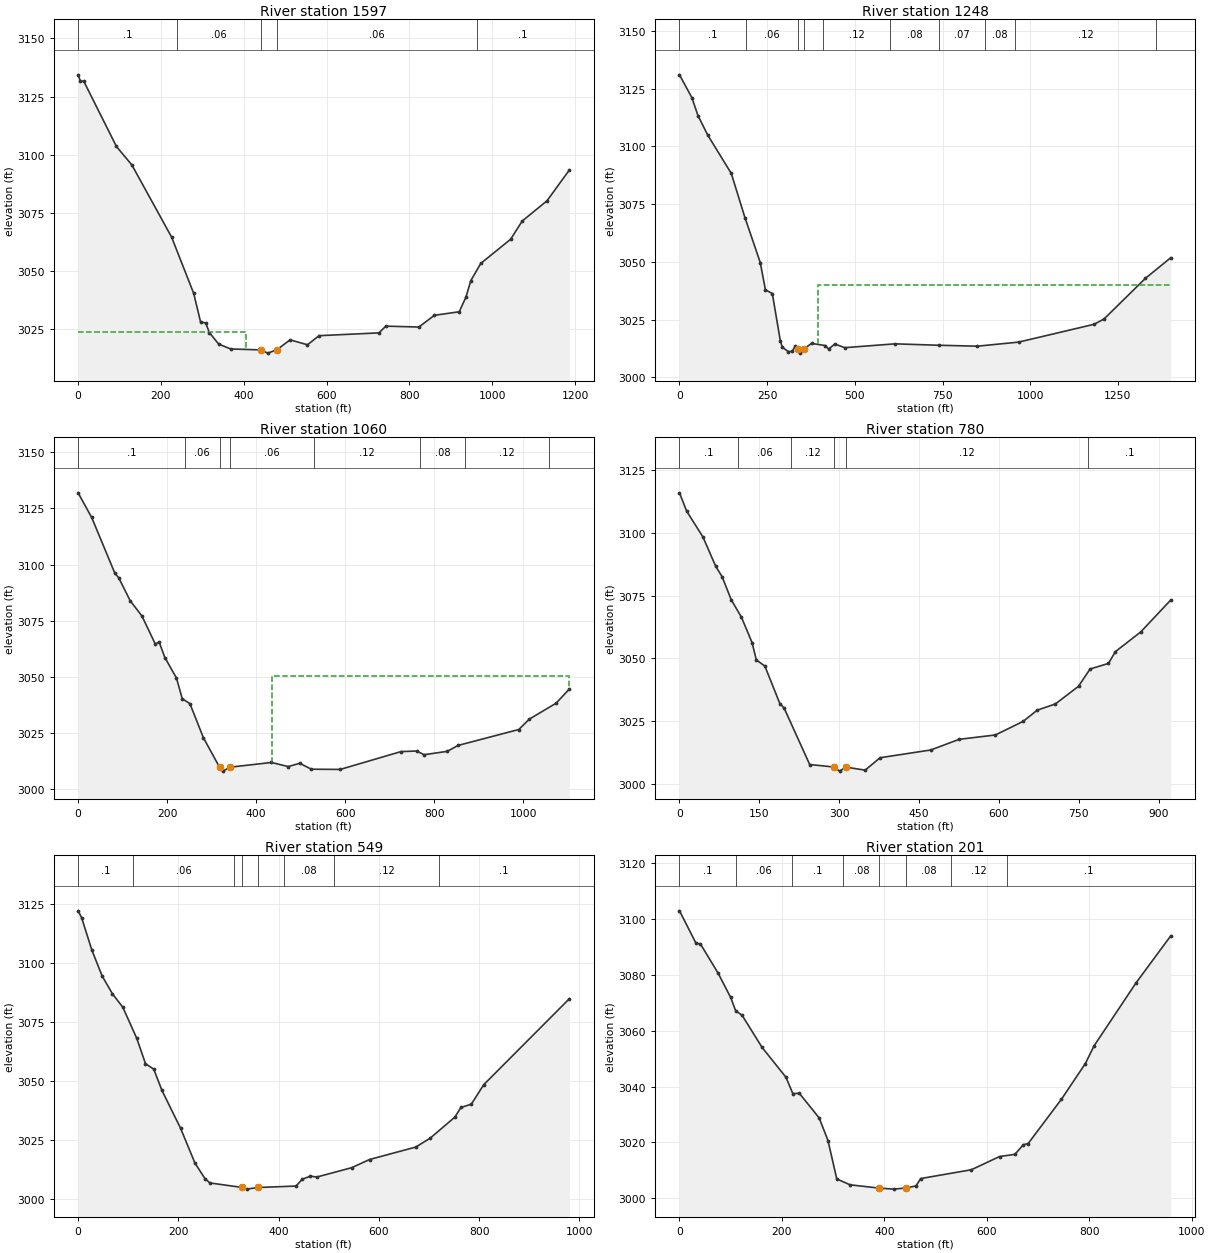
Type RM Length L Ch R = 1 ,1597    ,330.6,349.2,366.4
BEGIN DESCRIPTION:
Structure XS 2
END DESCRIPTION:
XS GIS Cut Line= 6
2347328.15146431710338.4666764652347411.69325983710032.595909002
 2347320.6577396709947.7864900152347196.10152946709655.310380853
2347224.39794407709569.0736887052347233.93543831709235.503524196
#Sta/Elev= 30
       0 3134.33     5.5 3131.64    13.8 3131.54    92.6 3103.54   129.9 3095.59
   225.8  3064.6   279.2 3040.39   295.7 3028.18   308.2 3027.71   317.1 3023.56
   339.5 3018.64   368.5 3016.55   441.5 3016.14   457.7 3014.76   479.4 3016.13
   511.9 3020.46   553.9 3018.35   581.9 3022.26   726.5 3023.46   743.1 3026.36
   822.9 3025.97   860.4 3031.01   920.4 3032.53   936.4 3038.75   948.4 3045.93
   972.4  3053.3  1044.5 3063.69  1072.5 3071.52  1132.3 3080.21  1186.2 3093.42
#Mann= 5 ,-1,0
       0      .1       0     240     .06       0   441.5    .045       0
   479.4     .06       0  962.48      .1       0
#XS Ineff= 2 , 0
          405.82 3024.05
Permanent Ineff=
       F       F
Bank Sta=441.5,479.4
XS Rating Curve= 0 ,0
Exp/Cntr(USF)=0,0
Exp/Cntr=0.3,0.1

Type RM Length L Ch R = 1 ,1248    ,181.7,187.2,187.5
BEGIN DESCRIPTION:
Structure XS 1
END DESCRIPTION:
XS GIS Cut Line= 3
2347358.36369535710333.8032853832348015.91847298709693.765335846
 2348099.4602685709218.116080716
#Sta/Elev= 30
       0 3130.94    35.3 3121.08    52.6 3113.33    80.7 3104.82   147.7 3088.26
   186.7 3069.12   230.3 3049.72     245 3037.92   264.7 3036.31   287.6 3015.75
   293.4 3013.05   310.6 3011.14   321.4 3011.32   329.8 3013.49   338.3 3012.24
     345 3010.52   354.2 3012.21   376.5 3014.73   414.7 3013.82   425.3  3012.3
     443 3014.48   471.1 3012.88   614.5 3014.54     740 3013.92   849.6 3013.53
     967 3015.29  1182.2    3023  1210.6 3025.31  1328.4 3042.88  1400.6 3051.78
#Mann= 10 ,-1,0
       0      .1       0     190     .06       0   338.3    .045       0
   354.2     .06       0     410     .12       0     600     .08       0
     740     .07       0     870     .08       0  957.62     .12       0
 1357.62     .06       0
#XS Ineff= 2 , 0
                          395.09         3040.07
Permanent Ineff=
       F       F
Bank Sta=338.3,354.2
XS Rating Curve= 0 ,0
Exp/Cntr(USF)=0,0
Exp/Cntr=0.3,0.1

Type RM Length L Ch R = 1 ,1060    ,276.4,280.9,284.9
XS GIS Cut Line= 3
2347372.00453014710352.3921574032348017.43227294710085.597391069
2348421.66676738710112.546357365
#Sta/Elev= 30
       0 3131.99    30.5    3121    82.4  3096.2    91.1 3094.15     117 3083.87
   143.5 3077.01   173.3 3064.58     182 3065.42     195  3058.5   220.9 3049.41
   233.9 3040.19   251.2 3037.93   281.5 3022.74  317.963009.519   324.8 3007.84
   342.1 3009.62   434.4  3011.7     472 3009.87   497.9 3011.34   523.9  3008.7
   588.8  3008.6   725.2 3016.55   760.7 3016.81   777.3 3015.16   829.4 3016.67
   853.5  3019.3     990 3026.41  1013.8 3031.06    1074 3038.16  1103.5 3044.47
#Mann= 8 ,-1,0
       0      .1       0     240     .06       0  317.96    .045       0
   342.1     .06       0     530     .12       0   768.4     .08       0
   868.4     .12       0  1058.4     .06       0
#XS Ineff= 2 , 0
                          434.95         3050.21
Permanent Ineff=
       F       F
Bank Sta=317.96,342.1
XS Rating Curve= 0 ,0
Exp/Cntr(USF)=0,0
Exp/Cntr=0.3,0.1

Type RM Length L Ch R = 1 ,780     ,227.5,230.8,230.2
XS GIS Cut Line= 3
2347384.13156497710469.6201607922347761.41709312710495.221678773
2348264.01531455710705.423615885
#Sta/Elev= 30
       0 3115.92    13.4 3108.65    44.1 3098.31    68.2 3086.57    80.2 3082.44
    97.2 3073.31   116.3  3066.4   136.4 3056.22   144.4 3049.31   160.4 3046.89
   188.5 3031.96   196.5 3030.19   244.6 3007.66   289.63006.665   300.7 3005.02
   312.8 3006.61   348.9 3005.41   376.9 3010.36   472.2 3013.45   525.4 3017.69
   593.6 3019.43   645.6 3024.85   672.2 3029.32   706.3 3031.79   749.7 3038.84
   771.4 3045.72     806 3047.94   818.9 3052.62   866.7 3060.51   922.9 3073.19
#Mann= 6 ,-1,0
       0      .1       0     110     .06       0     210     .12       0
   289.6    .045       0   312.8     .12       0  768.15      .1       0
Bank Sta=289.6,312.8
XS Rating Curve= 0 ,0
Exp/Cntr(USF)=0,0
Exp/Cntr=0.3,0.1

Type RM Length L Ch R = 1 ,549     ,338.3,347.6,349.1
XS GIS Cut Line= 2
2347289.48453846710614.7324616032348242.13049704710843.798675122
#Sta/Elev= 30
       0  3122.2     6.9 3119.36    27.5 3105.54      48 3094.59    68.6 3087.03
    89.2 3081.38     117 3068.22   134.4 3057.51   150.9 3055.16   167.3 3046.14
   204.4 3030.14   233.2 3015.36     253 3008.86   262.9    3007   327.8 3005.07
   335.9 3004.38   359.1 3005.07   434.7 3005.69   447.1 3008.57   463.5 3009.89
   475.9 3009.49   545.8 3013.46   581.3 3016.92   673.4 3022.18   702.1 3025.92
   751.5 3034.87   763.7 3038.97   784.4 3040.34   809.1  3048.6   979.8 3084.97
#Mann= 8 ,-1,0
       0      .1       0     110     .06       0     310      .1       0
   327.8    .045       0   359.1      .1       0     410     .08       0
     510     .12       0     720      .1       0
Bank Sta=327.8,359.1
XS Rating Curve= 0 ,0
Exp/Cntr(USF)=0,0
Exp/Cntr=0.3,0.1

Type RM Length L Ch R = 1 ,201     ,195.8,201.1,203.6
XS GIS Cut Line= 2
2347194.14135258710869.8123102922348087.49958531711218.801423829
#Sta/Elev= 30
       0 3102.92    32.2 3091.32    40.8 3091.09    75.2 3080.66    99.9 3071.91
   109.5 3067.22   122.4 3065.47   161.1 3054.05     208  3043.3   221.2 3037.49
   234.1 3037.56   272.7 3028.77   289.9 3020.68   307.1 3006.92   332.9 3004.82
   390.2 3003.63   418.7 3003.27     4423003.692   461.7  3004.4     471 3007.06
   569.9 3010.21   624.9 3014.94   654.9 3015.72   671.2 3019.15   680.7 3019.58
   745.8 3035.47   792.3 3048.19   809.5 3054.59   891.1 3077.05   959.1 3093.94
#Mann= 8 ,-1,0
       0      .1       0     110     .06       0     220      .1       0
     320     .08       0   390.2    .045       0     442     .08       0
     530     .12       0     640      .1       0
Bank Sta=390.2,442
XS Rating Curve= 0 ,0
Exp/Cntr(USF)=0,0
Exp/Cntr=0.3,0.1

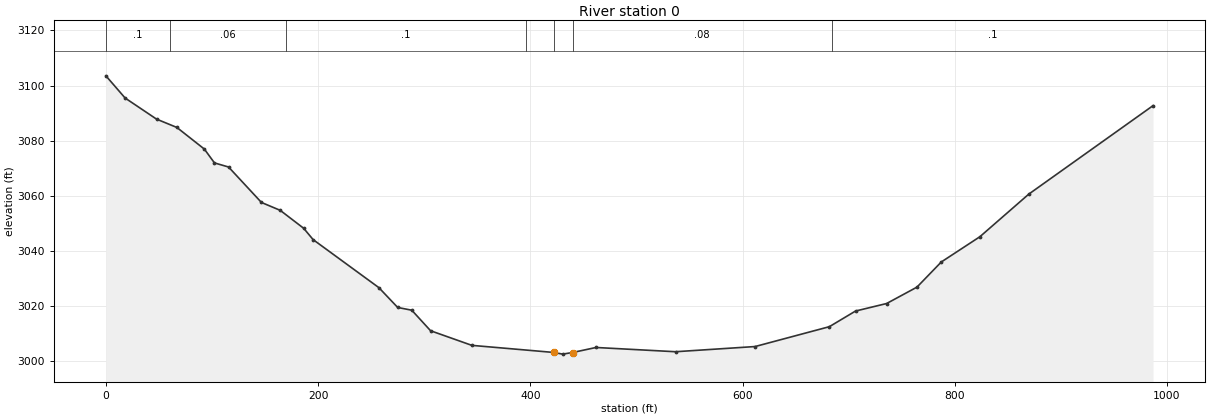
Type RM Length L Ch R = 1 ,0       ,650.9,647.2,641.8
XS GIS Cut Line= 4
2347143.78586515710985.9494808662347464.95947218711138.586442622
2347671.65535789711367.541885255 2347980.1092181711462.939986352
#Sta/Elev= 30
       0 3103.54    18.1 3095.49    47.7 3087.84    66.9 3084.81    92.8 3076.96
   102.3 3071.95   115.6 3070.46   146.6  3057.6   164.3 3054.74   186.4 3048.23
   195.3 3044.12   257.3 3026.69     275 3019.51   288.3 3018.51     306 3011.06
   344.9 3005.76  422.013003.189   430.5 3002.58   439.9 3003.17   461.9 3004.99
   536.9 3003.45   611.8 3005.33   681.8 3012.53   706.5 3018.21   735.8 3020.94
   764.4 3026.89   787.3    3036   823.7 3045.17   869.8 3060.63   986.9 3092.73
#Mann= 7 ,-1,0
       0      .1       0      60     .06       0     170      .1       0
   395.6     .08       0  422.01    .045       0   439.9     .08       0
  684.05      .1       0
Bank Sta=422.01,439.9
XS Rating Curve= 0 ,0
Exp/Cntr=0.3,0.1
LCMann Table=0

Chan Stop Cuts=-1
Use User Specified Reach Order=0
Composite Channel Slope=5